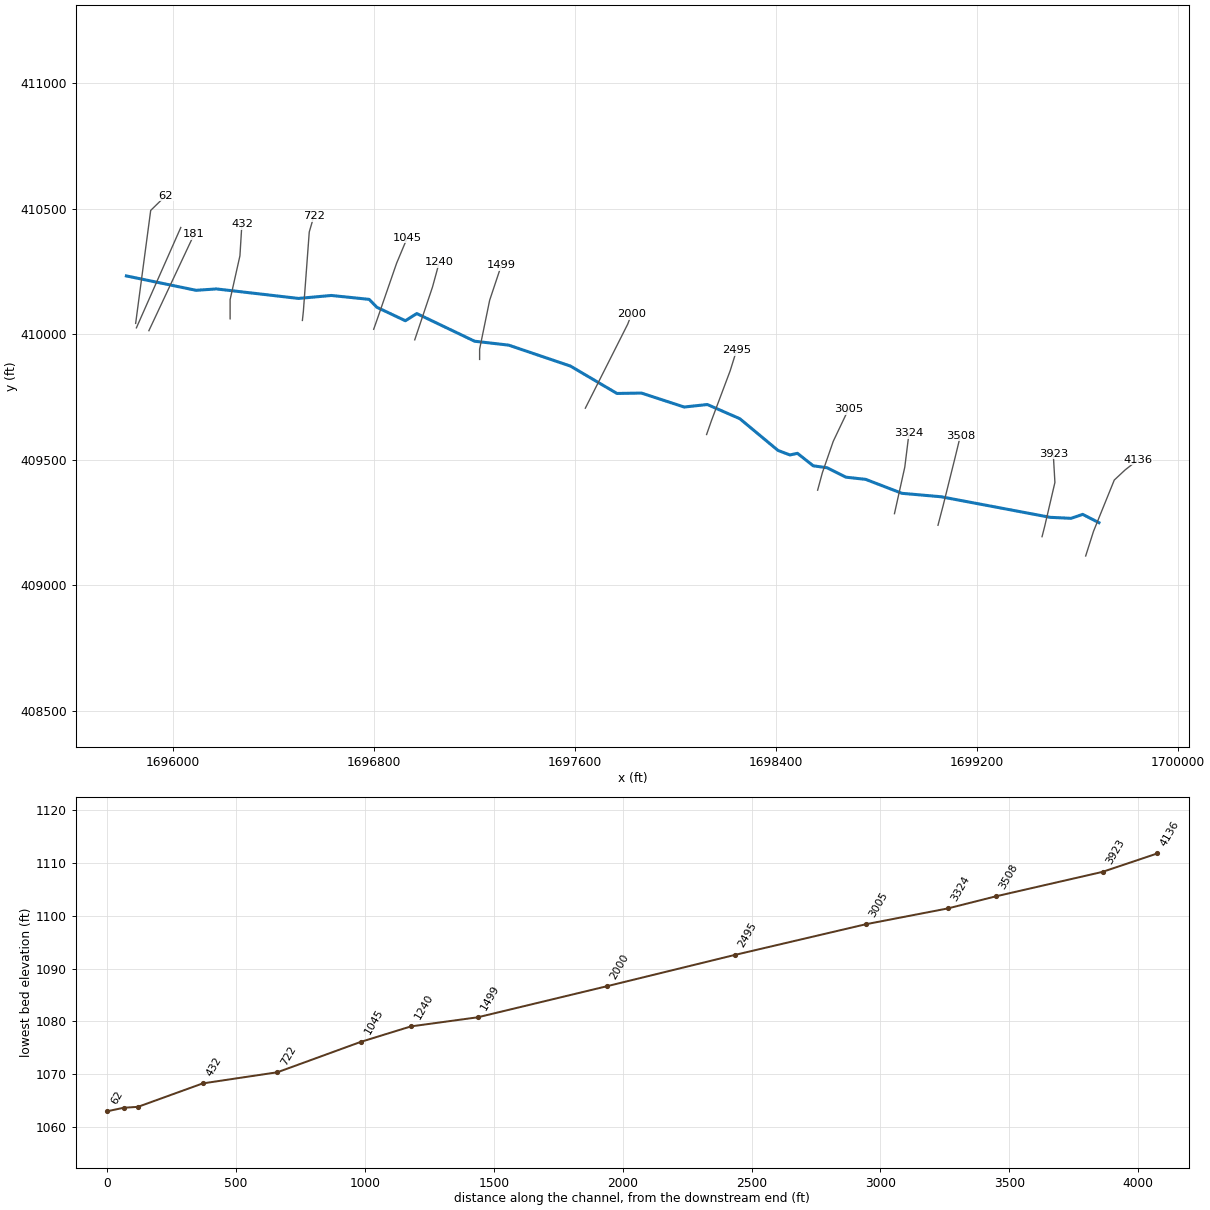
--- HGGNBTHMRN.prj (project) ---

Proj Title=HGGNBTHMRN
Current Plan=p01
Default Exp/Contr=0,0
English Units
Geom File=g01
Flow File=f01
Plan File=p01
BEGIN DESCRIPTION:
---------- MODELED AS PART OF WVEMD CTP PROGRAM, 2023----------
Stream Name: Higginbotham Run
Flood Zone:  AFH
Wetzel County, WV
HEC-RAS Version: RAS 6.3
Vertical Datum: NAVD88
Projection: NAD 1983 StatePlane West Virginia S FIPS 4702 (US Feet)
Terrain: 1-meter West Virginia FEMA R3 South Central (collected 2018-2020)
Land Use: 2019 NLCD
Hydrologic Method:
WV SIR2010-5033 regression equations
Additional Model Notes:
None
END DESCRIPTION:
DSS Export Rating Curves= 0
DSS Export Rating Curve Sorted= 0
DSS Export Volume Flow Curves= 0
DXF OffsetX= 0
DXF OffsetY= 0
DXF ScaleX= 0
DXF ScaleY= 0

--- HGGNBTHMRN.p01 (plan) ---

Plan Title=Floodplain
Program Version=6.30
Short Identifier=Floodplain
Geom File=g01
Flow File=f01
Subcritical Flow
K Sum by GR= 0
Std Step Tol= 0.01
Critical Tol= 0.01
Num of Std Step Trials= 20
Max Error Tol= 0.3
Flow Tol Ratio= 0.001
Split Flow NTrial= 30
Split Flow Tol= 0.02
Split Flow Ratio= 0.02
Log Output Level= 0
Friction Slope Method= 1
Unsteady Friction Slope Method= 2
Unsteady Bridges Friction Slope Method= 1
Parabolic Critical Depth
Global Vel Dist= 0 , 0 , 0
Global Log Level= 0
CheckData=False
Encroach Param=-1 ,0,0, 0
Mapping Interval=1HOUR
Computation Time Step Use Courant=        0
Computation Time Step Use Time Series=    0
Computation Time Step Count To Double=0
Computation Time Step Max Doubling=0
Computation Time Step Max Halving=0
Computation Time Step Residence Courant=0
Run HTab= 0
Run UNet= 0
Run Sediment= 0
Run PostProcess= 0
Run WQNet= 0
Run RASMapper=-1
UNET Theta= 0
UNET Theta Warmup= 0
UNET ZTol= 0
UNET ZSATol= 0
UNET MxIter= 0
UNET Max Iter WO Improvement= 0
UNET MaxInSteps= 0
UNET DtIC= 0
UNET DtMin= 0
UNET MaxCRTS= 0
UNET WFStab= 0
UNET SFStab= 0
UNET WFX= 1
UNET SFX= 1
UNET Gravity=32.17405
UNET 1D Methodology=Finite Difference
UNET DSS MLevel= 1
UNET Pardiso=0
UNET DZMax Abort= 0
UNET Use Existing IB Tables= 0
UNET Froude Reduction=False
UNET Froude Limit= 0
UNET Froude Power= 0
UNET D1 Cores= 0
UNET WindReference=Eulerian
UNET WindDragFormulation=Hsu (1988)
UNET D2 Coriolis=0
UNET D2 Cores= 0
UNET D2 Theta= 1
UNET D2 Theta Warmup= 1
UNET D2 Z Tol= 0.01
UNET D2 Volume Tol= 0.01
UNET D2 Max Iterations= 20
UNET D2 Equation= 0
UNET D2 RampUpFraction=0.1
UNET D2 TimeSlices= 1
UNET D2 Turbulence Formulation=Non-Conservative (original)
UNET D2 Eddy Viscosity=0.3
UNET D2 Transverse Eddy Viscosity=0.1
UNET D2 Smagorinsky Mixing=0
UNET D2 BCVolumeCheck=0
UNET D2 Cores=0
UNET D2 SolverType=PARDISO (Direct)
UNET D2 Minimum Iterations= 3
UNET D2 Maximum Iterations= 30
UNET D2 Restart Number= 10
UNET D2 Relaxation Coeff=1.3
UNET D2 SOR Precondition Iterations= 10
UNET D2 ILUT Maximum Fill= 8
UNET D2 ILUT Tolerance=1E-08
UNET D2 Convergence Tolerance=0.00001
UNET D1D2 MaxIter= 0
UNET D1D2 ZTol=0.01
UNET D1D2 QTol=0.1
UNET D1D2 MinQTol=1
Write IC File= 0
Write IC File at Fixed DateTime=0
Write IC File at Sim End=0
Echo Input=False
Echo Parameters=False
Echo Output=False
Write Detailed= 0
HDF Write Warmup=0
HDF Write Time Slices=0
HDF Flush=0
HDF Compression= 1
HDF Chunk Size= 1
HDF Spatial Parts= 1
HDF Use Max Rows=0
HDF Fixed Rows= 1
Calibration Method= 0
Calibration Iterations= 20
Calibration Max Change=0.05
Calibration Tolerance=0.2
Calibration Maximum=1.5
Calibration Minimum=0.5
Calibration Optimization Method= 1
WQ AD Non Conservative
WQ ULTIMATE=-1
WQ Max Comp Step=1HOUR
WQ Output Interval=15MIN
WQ Output Selected Increments= 0
WQ Output face flow=0
WQ Output face velocity=0
WQ Output face area=0
WQ Output face dispersion=0
WQ Output cell volume=0
WQ Output cell surface area=0
WQ Output cell continuity=0
WQ Output cumulative cell continuity=0
WQ Output face conc=0
WQ Output face dconc_dx=0
WQ Output face courant=0
WQ Output face peclet=0
WQ Output face adv mass=0
WQ Output face disp mass=0
WQ Output cell mass=0
WQ Output cell source sink temp=0
WQ Output nsm pathways=0
WQ Output nsm derived pathways=0
WQ Create Restart=0
WQ Fixed Restart=0
WQ System Summary=0
WQ Write To DSS=0
Sorting and Armoring Iterations= 10
XS Update Threshold= 0.02
Bed Roughness Predictor= 0
Hydraulics Update Threshold= 0.02
Energy Slope Method= 1
Volume Change Method= 1
Sediment Retention Method= 0
Sediment TS Multiplier= 1
Warm Up Method= 0
XS Weighting Method= 0
Number of US Weighted Cross Sections= 1
Number of DS Weighted Cross Sections= 1
Upstream XS Weight=0
Main XS Weight=1
Downstream XS Weight=0
Number of DS XS's Weighted with US Boundary= 1
Upstream Boundary Weight= 1
Weight of XSs Associated with US Boundary= 0
Number of US XS's Weighted with DS Boundary= 1
Downstream Boundary Weight= 0.5
Weight of XSs Associated with DS Boundary= 0.5
Percentile Method= 0
Sediment Output Level= 3
Mass or Volume Output= 0
Output Increment Type= 1
Profile and TS Output Increment= 1
Transport Output Increment 1
XS Output Flag= 0
XS Output Increment= 10
Read HDF5 Sediment Hotstart= 0
Sediment Hotstart Type= 0
Write Gradation File= 0
Read Gradation Hotstart= 0
Write HDF5 File= 1
Write Binary Output= 1
Write DSS Sediment File= 0
DSS Sediment Output Type= 1
SV Curve= 0
Specific Gage Flag= 0
Subcell Erosion Methods= 0
Subcell Deposition Methods= 0
Advection Scheme= 1
Matrix Solver= 0
Implicit Weighting Factor= 1
Maximum Outer Loop Convergence Iterations= 5
Convergence Maximum Absolute= 0.001
Convergence RMSE= 0.0001
Grain Fractions Max Abs Error= 0.001
Max Subgrid Regions= 1
Max Subgrid Length Scale= 3.402823E+38
Initial Layer Thickness= 3.402823E+38
Min Layer Thickness= 3.402823E+38
Max Layer Thickness= 3.402823E+38
Number of Layers= 5

--- HGGNBTHMRN.f01 (steady flow) ---

Flow Title=Flow
Program Version=6.30
Number of Profiles= 1
Profile Names=F01pct
River Rch & RM=HGGNBTHMRN,Main            ,4136
     645
River Rch & RM=HGGNBTHMRN,Main            ,2495
     727
Boundary for River Rch & Prof#=HGGNBTHMRN,Main            , 1
Up Type= 0
Dn Type= 3
Dn Slope=0.0103
DSS Import GetInterval= 0
DSS Import GetPeak= 0
DSS Import FillOption= 0

--- HGGNBTHMRN.g01 (geometry) ---

Geom Title=Geometry
Program Version=6.30

River Reach=HGGNBTHMRN      ,Main
Reach XY= 30
1699684.27723316409248.5425829861699619.67919416409281.712556045
     1699573.492      409265.892     1699490.229      409269.931
     1699055.586      409351.951     1698900.556      409365.621
      1698756.09      409421.233     1698677.487      409429.931
     1698602.302      409467.524     1698547.312      409475.291
     1698484.554         409525.     1698454.729      409518.476
     1698407.195      409536.495     1698255.272      409662.942
     1698126.028      409719.486     1698033.756      409709.545
     1697863.813      409765.156      1697766.26      409763.603
     1697581.404      409872.652     1697335.345      409956.225
     1697199.888      409971.759     1696969.673      410082.051
     1696924.313      410053.469     1696810.604      410107.217
     1696780.157      410138.595     1696629.477      410154.129
     1696498.991      410142.323     1696172.154      410180.227
     1696091.688      410174.634      1695814.11      410231.988

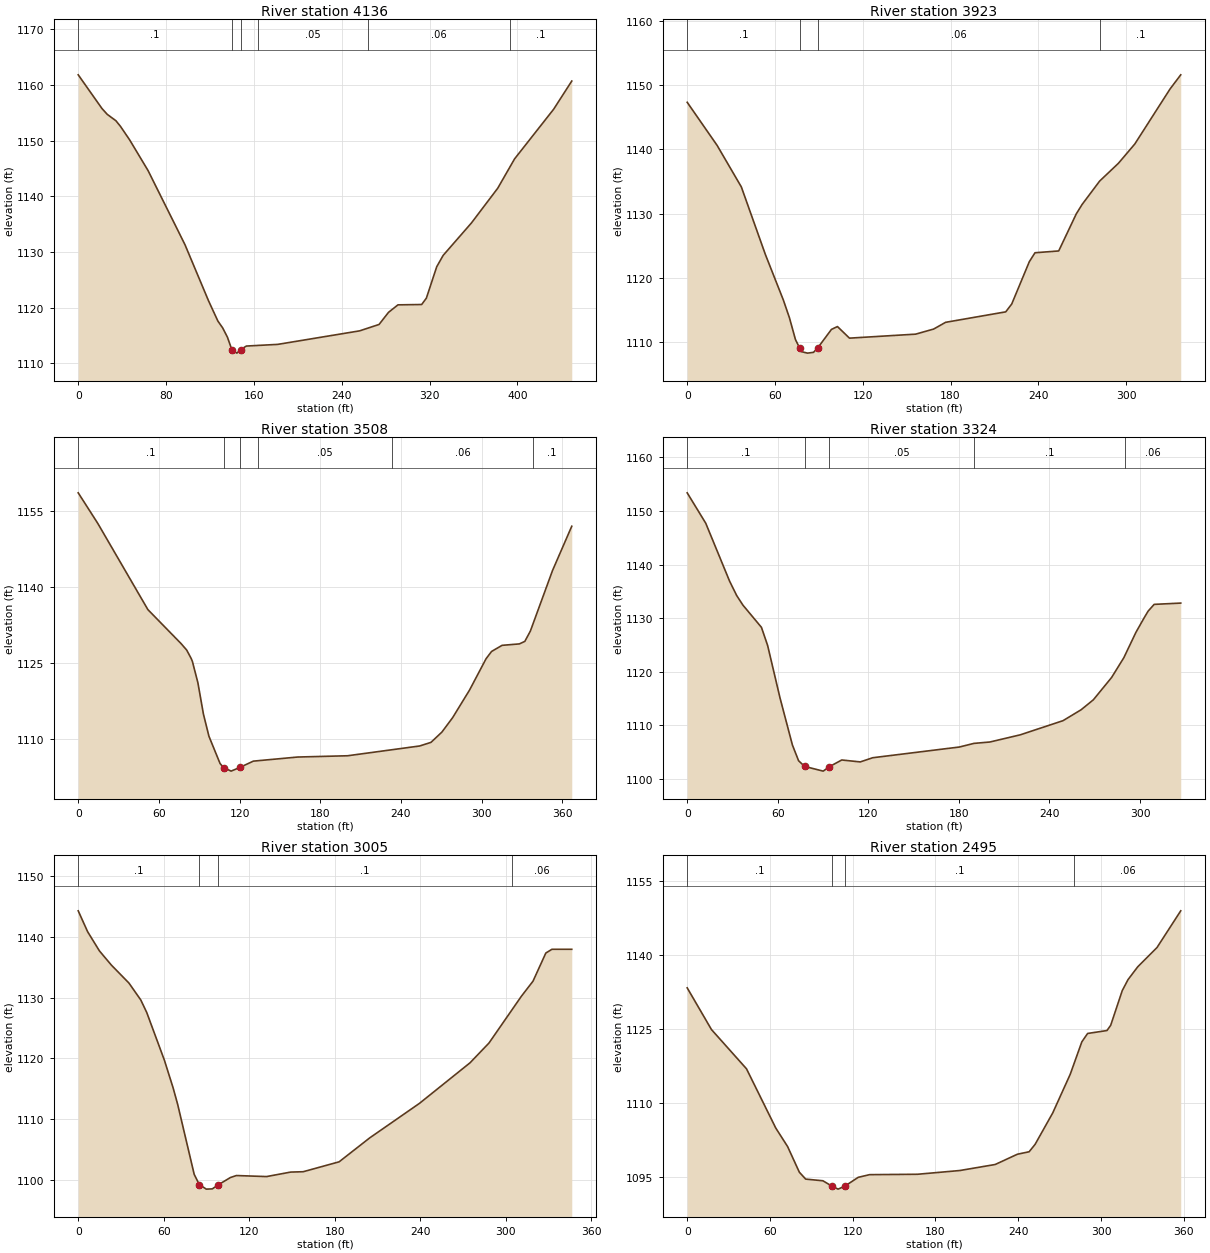
Type RM Length L Ch R = 1 ,4136    ,213.2,213.2,213.2
XS GIS Cut Line= 5
1699631.48310261409115.876574287 1699662.7900488409214.540889556
 1699745.3265433409418.510387468 1699788.9665289 409459.30428705
1699841.14477256409500.098186632
#Sta/Elev= 30
       0 1161.81    21.7 1155.74    26.5  1154.7    34.3 1153.57    38.5 1152.55
    46.9 1150.11    63.6 1144.62    97.2 1131.32   118.6 1121.27   127.2 1117.59
   131.6 1116.35   135.9 1114.69   139.9 1112.46   144.5 1111.83   147.9 1112.46
   153.1  1113.1   181.7  1113.4   256.3 1115.83     274 1116.98   282.6 1119.15
   291.2  1120.5   312.8 1120.56   317.1 1121.71   326.5 1127.34   332.4 1129.39
   358.1  1135.2   382.1 1141.45   397.4 1146.71     433 1155.63   449.5 1160.69
#Mann= 6 ,-1,0
       0      .1       0   139.9    .045       0   147.9      .1       0
  163.51     .05       0  263.51     .06       0  393.29      .1       0
Bank Sta=139.9,147.9
XS Rating Curve= 0 ,0
Exp/Cntr(USF)=0,0
Exp/Cntr=0.3,0.1

Type RM Length L Ch R = 1 ,3923    ,414.6,414.6,414.6
XS GIS Cut Line= 4
1699457.87185555409192.7208967561699468.30750428409233.514796338
1699509.10140386409409.0234340761699502.46053649409523.815570111
#Sta/Elev= 30
       0 1147.34    20.5 1140.62      37 1134.18    53.4 1123.69    65.7  1116.6
    69.9 1113.81      74 1110.43    76.91109.107    78.1 1108.56    82.2 1108.33
    86.3 1108.45    89.21109.143    98.6 1112.02   102.7 1112.46   110.9 1110.66
   156.1 1111.28   168.4 1112.07   176.6 1113.12   217.7 1114.75   221.8 1115.97
   233.8 1122.54   237.7 1123.94   253.9 1124.22   265.9 1129.98   269.9 1131.45
   281.9 1135.09   294.7 1137.85   305.9 1140.85     330 1149.41   337.3 1151.61
#Mann= 4 ,-1,0
       0      .1       0    76.9    .045       0    89.2     .06       0
  282.29      .1       0
Bank Sta=76.9,89.2
XS Rating Curve= 0 ,0
Exp/Cntr(USF)=0,0
Exp/Cntr=0.3,0.1

Type RM Length L Ch R = 1 ,3508    ,184.5,184.5,184.5
XS GIS Cut Line= 4
1699043.80609414409238.3869868141699064.88821279409319.201774962
1699111.73736534409507.7696139731699132.81948399409594.440546189
#Sta/Elev= 30
       0 1158.58    14.6 1152.53    51.8 1135.55    76.6 1128.81    80.7 1127.55
      84 1125.91    84.9 1125.33      89 1121.11    93.1 1114.95    97.2 1110.57
   105.5 1105.18   108.11104.394   113.7 1103.69   120.3 1104.43   130.2 1105.66
   163.2 1106.47   200.3 1106.72   253.9 1108.65   262.3 1109.36   270.4 1111.38
   278.4 1114.23     291 1119.68   303.3 1125.87   307.4  1127.3   315.2  1128.5
     328 1128.78   332.1 1129.28   336.2  1131.3   352.7 1143.26     367 1151.99
#Mann= 6 ,-1,0
       0      .1       0   108.1    .045       0   120.3      .1       0
  133.52     .05       0  233.52     .06       0  337.82      .1       0
Bank Sta=108.1,120.3
XS Rating Curve= 0 ,0
Exp/Cntr(USF)=0,0
Exp/Cntr=0.3,0.1

Type RM Length L Ch R = 1 ,3324    ,318.6,318.6,318.6
XS GIS Cut Line= 3
1698870.58135259409284.5334020751698911.69148395409470.056046171
1698928.55717887409606.035711445
#Sta/Elev= 30
       0 1153.39    12.3 1147.71    28.1 1136.89    32.8 1134.21    36.9 1132.43
    49.2 1128.27    53.3 1124.88    61.5 1115.09    69.7 1106.31    73.8 1103.36
    77.8  1102.3    90.1 1101.42    94.2 1102.25   102.4  1103.5   114.7 1103.14
   122.9 1103.92   180.3 1105.92     190  1106.6   200.6 1106.86   220.7  1108.2
     249 1110.84     261 1112.88   269.1 1114.74   281.2 1118.91   289.3  1122.6
   297.3 1127.33   302.8 1130.07   305.4  1131.3   309.4 1132.56     327  1132.8
#Mann= 5 ,-1,0
       0      .1       0    77.8    .045       0    94.2     .05       0
     190      .1       0  290.02     .06       0
Bank Sta=77.8,94.2
XS Rating Curve= 0 ,0
Exp/Cntr(USF)=0,0
Exp/Cntr=0.3,0.1

Type RM Length L Ch R = 1 ,3005    ,509.9,509.9,509.9
XS GIS Cut Line= 4
1698564.86219598409378.1525982961698583.65969546409447.558750221
1698627.02662378409572.9772605841698687.83222331409701.025581487
#Sta/Elev= 30
       0 1144.31     6.6 1140.87    14.9  1137.7    23.2 1135.38    35.6  1132.4
    43.9 1129.62    48.1 1127.54    60.5 1119.67    66.6 1115.12    69.8  1112.4
    81.4 1100.86      851099.165    89.9 1098.42    94.1 1098.46    98.3 1099.13
   106.8 1100.33     111 1100.66   132.2 1100.49   149.1 1101.23   157.9 1101.29
   183.1 1102.92   204.6 1106.87   239.5 1112.56     275 1119.25   288.3 1122.51
     311 1130.21   319.2 1132.71   328.2 1137.35   332.5 1137.97   346.4 1137.97
#Mann= 4 ,-1,0
       0      .1       0      85    .045       0    98.3      .1       0
  304.61     .06       0
Bank Sta=85,98.3
XS Rating Curve= 0 ,0
Exp/Cntr(USF)=0,0
Exp/Cntr=0.3,0.1

Type RM Length L Ch R = 1 ,2495    ,495.7,495.7,495.7
XS GIS Cut Line= 4
1698122.98731531 409599.923444471698142.50779554409655.882154459
1698216.68562041409853.6896874451698242.71292738409936.977069755
#Sta/Elev= 30
       0 1133.36    17.6 1124.91      43 1116.96    64.2 1104.97    72.8 1101.21
    81.3 1096.02    85.9 1094.62    98.4 1094.28   104.91093.199   109.4 1092.59
   114.3  1093.2     124 1094.98   132.2 1095.52     167  1095.6   197.7 1096.36
   223.3 1097.58   239.4 1099.66   247.9 1100.16   252.2 1101.65     265 1108.02
   277.7 1115.86   286.1 1122.42   290.3 1124.12   304.3 1124.71     307 1125.76
   315.4  1132.8   319.6 1135.03   326.6 1137.61   340.6 1141.53   357.8 1148.96
#Mann= 4 ,-1,0
       0      .1       0   104.9    .045       0   114.3      .1       0
  280.52     .06       0
Bank Sta=104.9,114.3
XS Rating Curve= 0 ,0
Exp/Cntr(USF)=0,0
Exp/Cntr=0.3,0.1

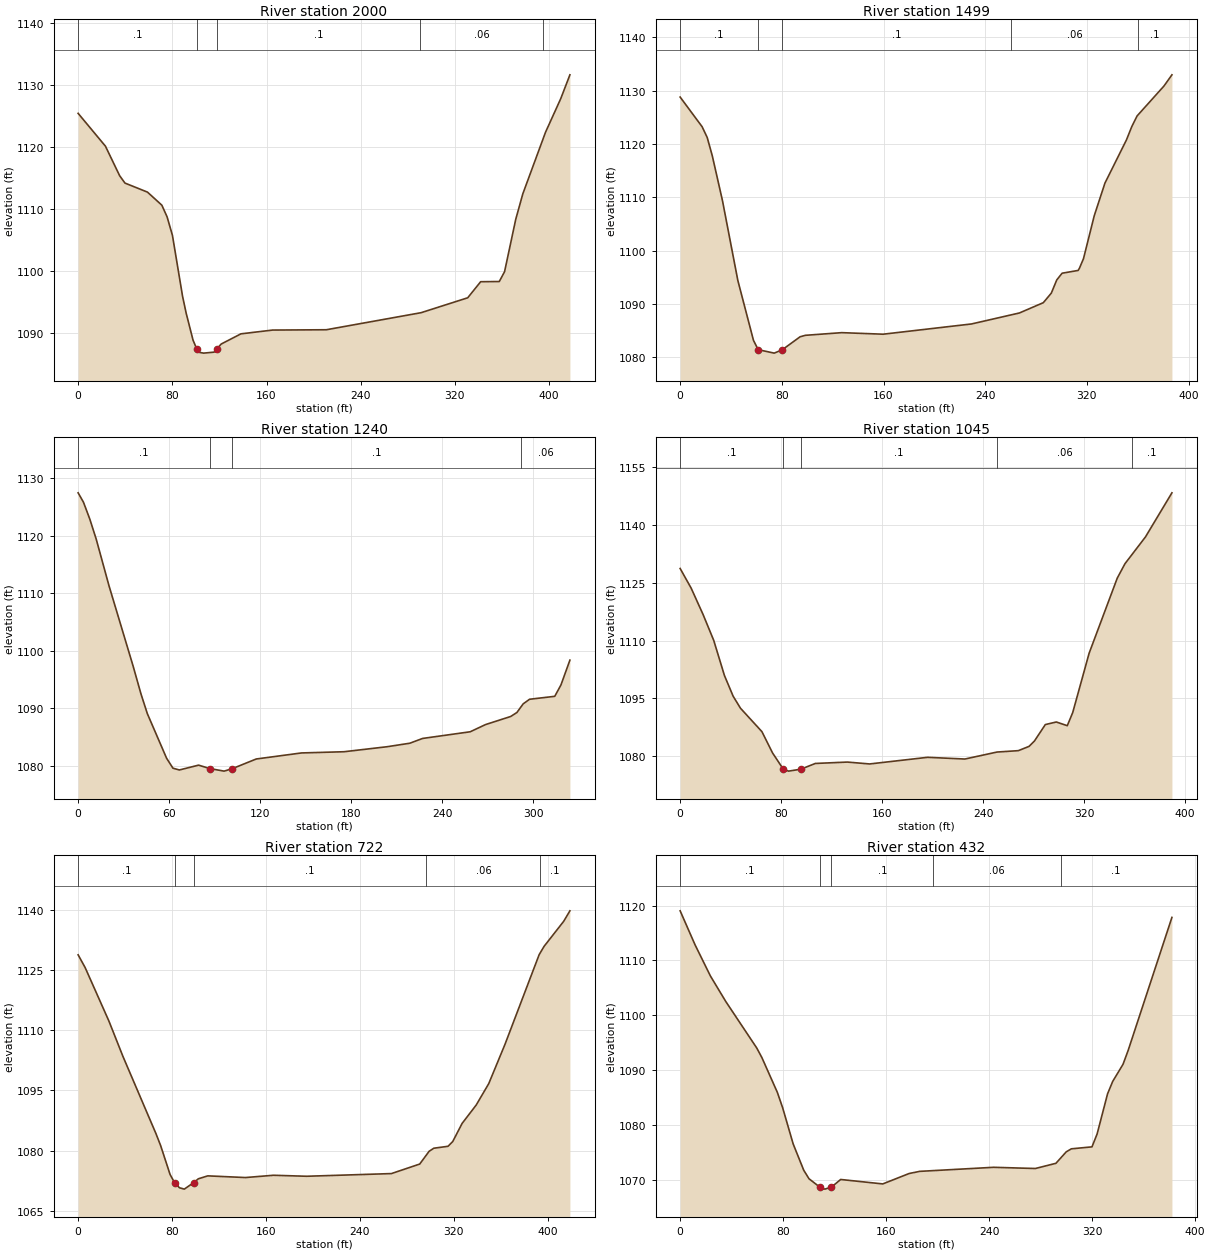
Type RM Length L Ch R = 1 ,2000    ,500.9,500.9,500.9
XS GIS Cut Line= 3
1697640.50199659409705.0235383561697809.15894577410039.994979084
1697824.38492034410079.816758751
#Sta/Elev= 30
       0 1125.45    23.2 1120.14    35.3 1115.35    39.8 1114.17    58.9 1112.71
    71.1  1110.6    75.6 1108.69    80.1 1105.72    88.7 1095.87    91.7 1093.18
    97.6 1088.77   100.6 1087.41   102.5 1086.81   106.6 1086.67   115.5 1086.83
   118.11087.398   121.5 1088.14   138.3 1089.79   165.2  1090.4   210.8 1090.45
   291.3 1093.21   330.9 1095.62   341.9 1098.22   357.7 1098.25   362.2 1099.84
   371.7 1108.32   377.7 1112.43     397  1122.4   409.9 1127.82   417.7 1131.68
#Mann= 5 ,-1,0
       0      .1       0   100.6    .045       0   118.1      .1       0
     290     .06       0  395.03      .1       0
Bank Sta=100.6,118.1
XS Rating Curve= 0 ,0
Exp/Cntr(USF)=0,0
Exp/Cntr=0.3,0.1

Type RM Length L Ch R = 1 ,1499    ,258.9,258.9,258.9
XS GIS Cut Line= 4
1697219.73117405409899.2214742751697219.73117405409940.331605637
1697259.78719948410135.341203123 1697306.1678605410274.483186195
#Sta/Elev= 30
       0 1128.82    17.3 1123.25    21.3 1121.23    25.3 1117.79    33.3 1109.39
    45.4 1094.41    57.7 1083.18    61.4 1081.44      74 1080.79    80.31081.413
    94.4 1083.86    98.5 1084.13   127.1 1084.63   159.7 1084.34   229.2 1086.26
   266.9 1088.32   285.7 1090.25     292 1092.04   296.3 1094.52   300.5 1095.78
   313.1  1096.3   314.1  1096.7   317.3 1098.49   325.8 1106.57   334.2 1112.68
   351.1 1120.77   355.3 1123.27   359.5 1125.28   380.6 1130.88   386.9 1132.99
#Mann= 5 ,-1,0
       0      .1       0    61.4    .045       0    80.3      .1       0
  260.19     .06       0  360.19      .1       0
Bank Sta=61.4,80.3
XS Rating Curve= 0 ,0
Exp/Cntr(USF)=0,0
Exp/Cntr=0.3,0.1

Type RM Length L Ch R = 1 ,1240    ,194.5,194.5,194.5
XS GIS Cut Line= 3
1696961.55252172409977.2650179261697032.24929839410187.818461491
1697059.14481125410286.179194252
#Sta/Elev= 30
       0 1127.44     3.5 1125.82     7.7 1122.87    11.9 1119.41    20.3 1111.33
    36.2 1097.36    41.4 1092.51    45.6 1089.07    58.3 1081.31    62.5 1079.58
    66.7 1079.27    79.4 1080.11    86.7 1079.52    96.2 1079.07   101.61079.499
   117.4 1081.18   147.2 1082.23   175.2 1082.44   203.6 1083.31   218.6 1083.92
     227 1084.75   258.4 1085.91   268.5 1087.16   285.1 1088.57   289.2 1089.27
   293.3 1090.76   297.5 1091.56   314.1 1092.07   318.2 1094.05   324.1 1098.36
#Mann= 4 ,-1,0
       0      .1       0    86.7    .045       0   101.6      .1       0
  292.11     .06       0
Bank Sta=86.7,101.6
XS Rating Curve= 0 ,0
Exp/Cntr(USF)=0,0
Exp/Cntr=0.3,0.1

Type RM Length L Ch R = 1 ,1045    ,323.9,323.9,323.9
XS GIS Cut Line= 4
1696798.18406795410019.3974289711696815.10181748410067.547946869
1696889.27964235410282.2732293871696932.22469885410385.081091926
#Sta/Elev= 30
       0 1128.72     8.7 1123.63    18.1 1116.83    26.6 1110.07    35.1 1100.94
      42 1095.57    47.8 1092.46    64.8 1086.38    73.2 1080.86    81.7 1076.66
    85.9 1076.14    95.6 1076.64   107.1 1078.13   132.5 1078.49   150.1    1078
     196 1079.72   225.6 1079.28     251 1081.09   267.9 1081.45   276.4 1082.56
   280.7 1083.96   289.3 1088.22     298 1088.89   306.7 1087.93     311 1091.33
     324 1106.73   346.3 1126.22   352.4 1129.96   368.6 1136.89   389.6 1148.35
#Mann= 5 ,-1,0
       0      .1       0    81.7    .045       0    95.6      .1       0
  251.04     .06       0  358.21      .1       0
Bank Sta=81.7,95.6
XS Rating Curve= 0 ,0
Exp/Cntr(USF)=0,0
Exp/Cntr=0.3,0.1

Type RM Length L Ch R = 1 ,722     ,289.6,289.6,289.6
XS GIS Cut Line= 4
1696514.48642195410054.534293383  1696518.390518410090.972523144
1696541.81509428410407.2043028521696560.03420916410469.669839584
#Sta/Elev= 30
       0 1128.86       6 1125.66    26.2 1112.34    38.2 1103.48    66.3 1084.22
    70.3 1081.22    78.3 1074.04    82.11071.998    86.3 1070.72    90.4 1070.38
    98.4    1072   102.4 1072.96   110.4 1073.69   142.5 1073.27   166.4 1073.84
   194.6 1073.59   266.8 1074.26   290.9 1076.64   298.9 1079.82   302.9 1080.59
     315 1081.07     319 1082.25     327 1086.78     339 1091.37   349.7 1096.72
   363.5 1106.51   392.6 1128.89   396.8 1130.97   413.5 1137.22   418.8 1139.84
#Mann= 5 ,-1,0
       0      .1       0    82.1    .045       0    98.4      .1       0
  296.65     .06       0  393.74      .1       0
Bank Sta=82.1,98.4
XS Rating Curve= 0 ,0
Exp/Cntr(USF)=0,0
Exp/Cntr=0.3,0.1

Type RM Length L Ch R = 1 ,432     ,251.4,251.4,251.4
XS GIS Cut Line= 4
1696226.88467992410061.0411201261696226.88467992410137.821675693
1696265.92564037410312.2046324051696273.73383247410438.437071218
#Sta/Elev= 30
       0 1119.03    11.5 1112.87    23.5 1107.15    35.5 1102.47    59.5 1094.01
    63.5 1092.26    75.5 1085.92    79.6 1083.13    87.8 1076.51      96 1071.72
   100.1 1070.16   108.3 1068.67   112.4 1068.27   117.51068.636   124.7 1070.03
   157.4 1069.22   177.9 1071.12   186.1 1071.51   243.5 1072.25   275.9 1072.03
   291.9 1072.98   299.9 1075.07   303.9 1075.62   319.9 1075.98   323.9 1078.34
     332 1085.65     336 1087.92     344 1091.03     348 1093.57     382 1117.83
#Mann= 5 ,-1,0
       0      .1       0   108.3    .045       0   117.5      .1       0
  196.78     .06       0  295.48      .1       0
Bank Sta=108.3,117.5
XS Rating Curve= 0 ,0
Exp/Cntr(USF)=0,0
Exp/Cntr=0.3,0.1

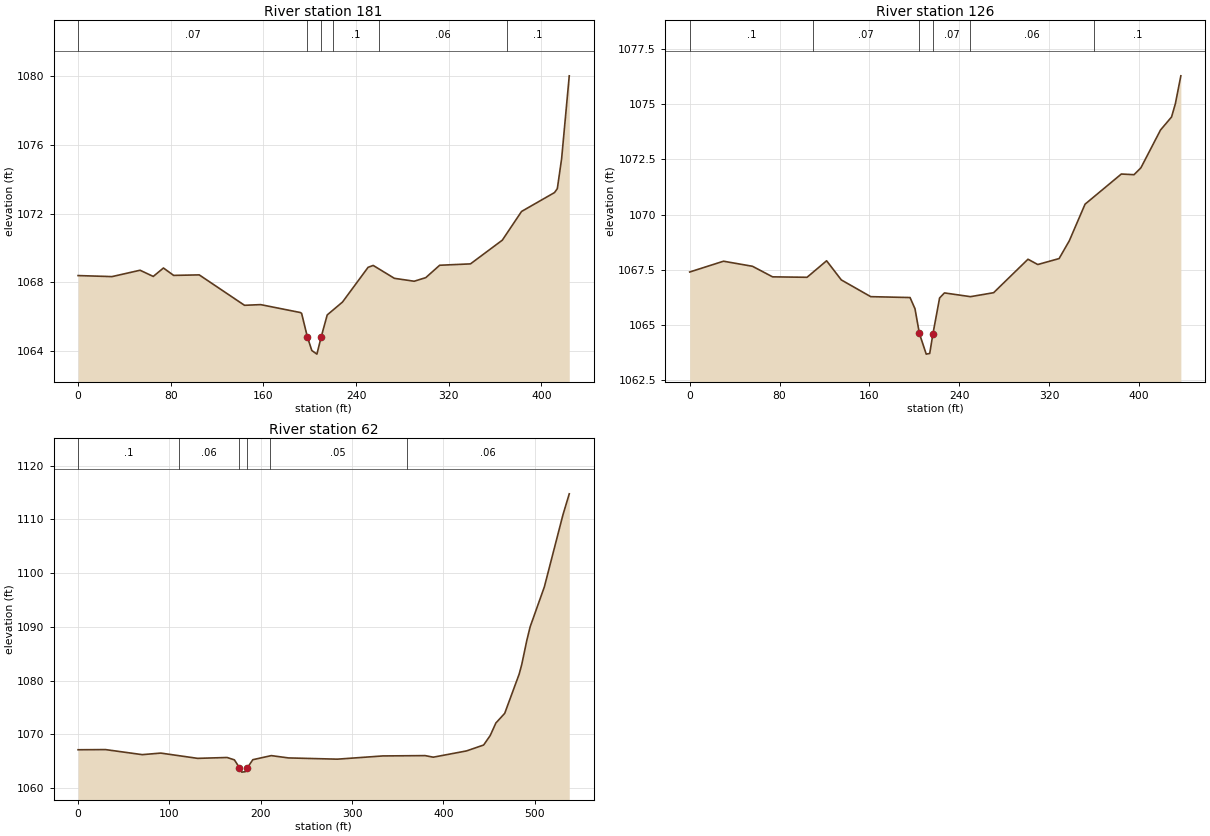
Type RM Length L Ch R = 1 ,181     ,55,55,55
XS GIS Cut Line= 2
1695903.69358751410013.7974694851696083.63546287410397.780578513
#Sta/Elev= 30
       0  1068.4    29.3 1068.34    53.5 1068.71    64.9 1068.35    73.7 1068.84
    82.5 1068.41   104.6 1068.44   143.7 1066.67   157.6 1066.71   191.9 1066.25
     193  1066.2   197.9 1064.85   201.8 1064.04   206.2 1063.83   209.9 1064.83
   215.1 1066.11   228.3 1066.86   250.4 1068.88   254.8 1068.99   273.1 1068.24
   290.2 1068.07   300.2 1068.28   312.2    1069   338.8 1069.08   366.3 1070.46
   382.9 1072.13   411.4 1073.23   413.8 1073.46   417.5  1075.2   424.1 1080.02
#Mann= 6 ,-1,0
       0     .07       0   197.9    .045       0   209.9     .07       0
     220      .1       0     260     .06       0     370      .1       0
Bank Sta=197.9,209.9
XS Rating Curve= 0 ,0
Exp/Cntr(USF)=0,0
Exp/Cntr=0.3,0.1

Type RM Length L Ch R = 1 ,126     ,63.9,63.9,63.9
XS GIS Cut Line= 2
1695853.88824701410025.0438366951696030.61687459410425.093184595
#Sta/Elev= 30
       0 1067.39    30.1 1067.88    55.9 1067.65    73.8 1067.17   104.5 1067.15
   121.9  1067.9     135 1067.03   161.2 1066.27   196.2 1066.23   200.6 1065.72
   204.5  1064.6   210.6 1063.66   213.7 1063.69   216.6 1064.59   222.5 1066.21
   226.8 1066.44     250 1066.27   270.6 1066.45   301.2 1067.97   309.9 1067.73
   328.9    1068     338 1068.81     352 1070.47   384.3 1071.84   395.6 1071.81
   401.7 1072.12   419.2 1073.84     429 1074.43   432.4 1075.03   437.3  1076.3
#Mann= 6 ,-1,0
       0      .1       0     110     .07       0   204.5    .045       0
   216.6     .07       0     250     .06       0     360      .1       0
Bank Sta=204.5,216.6
XS Rating Curve= 0 ,0
Exp/Cntr(USF)=0,0
Exp/Cntr=0.3,0.1

Type RM Length L Ch R = 1 ,62      ,,,
XS GIS Cut Line= 3
1695850.94718629410042.8023687321695910.80999232410493.074779345
1695970.67279836410551.636220031
#Sta/Elev= 30
       0 1067.16      30 1067.19    70.3 1066.25    90.5 1066.54   130.9 1065.56
   163.2 1065.72   171.2 1065.28   176.71063.838   179.3    1063   183.3 1063.08
   185.31063.787   191.4 1065.31   211.6 1066.07   230.5 1065.64     284 1065.41
   333.8 1066.01   380.1 1066.07   389.1 1065.78   425.4 1066.94   444.2 1068.04
   451.4  1069.8   457.6 1072.13   467.3 1073.93   483.1 1081.21   485.9 1082.97
   491.5 1087.49   495.2 1090.04   510.7 1097.43   531.1 1110.85     538 1114.74
#Mann= 6 ,-1,0
       0      .1       0     110     .06       0   176.7    .045       0
   185.3     .06       0     210     .05       0     360     .06       0
Bank Sta=176.7,185.3
XS Rating Curve= 0 ,0
Exp/Cntr(USF)=0,0
Exp/Cntr=0.3,0.1
LCMann Table=0

Chan Stop Cuts=-1
Use User Specified Reach Order=0
Composite Channel Slope=5